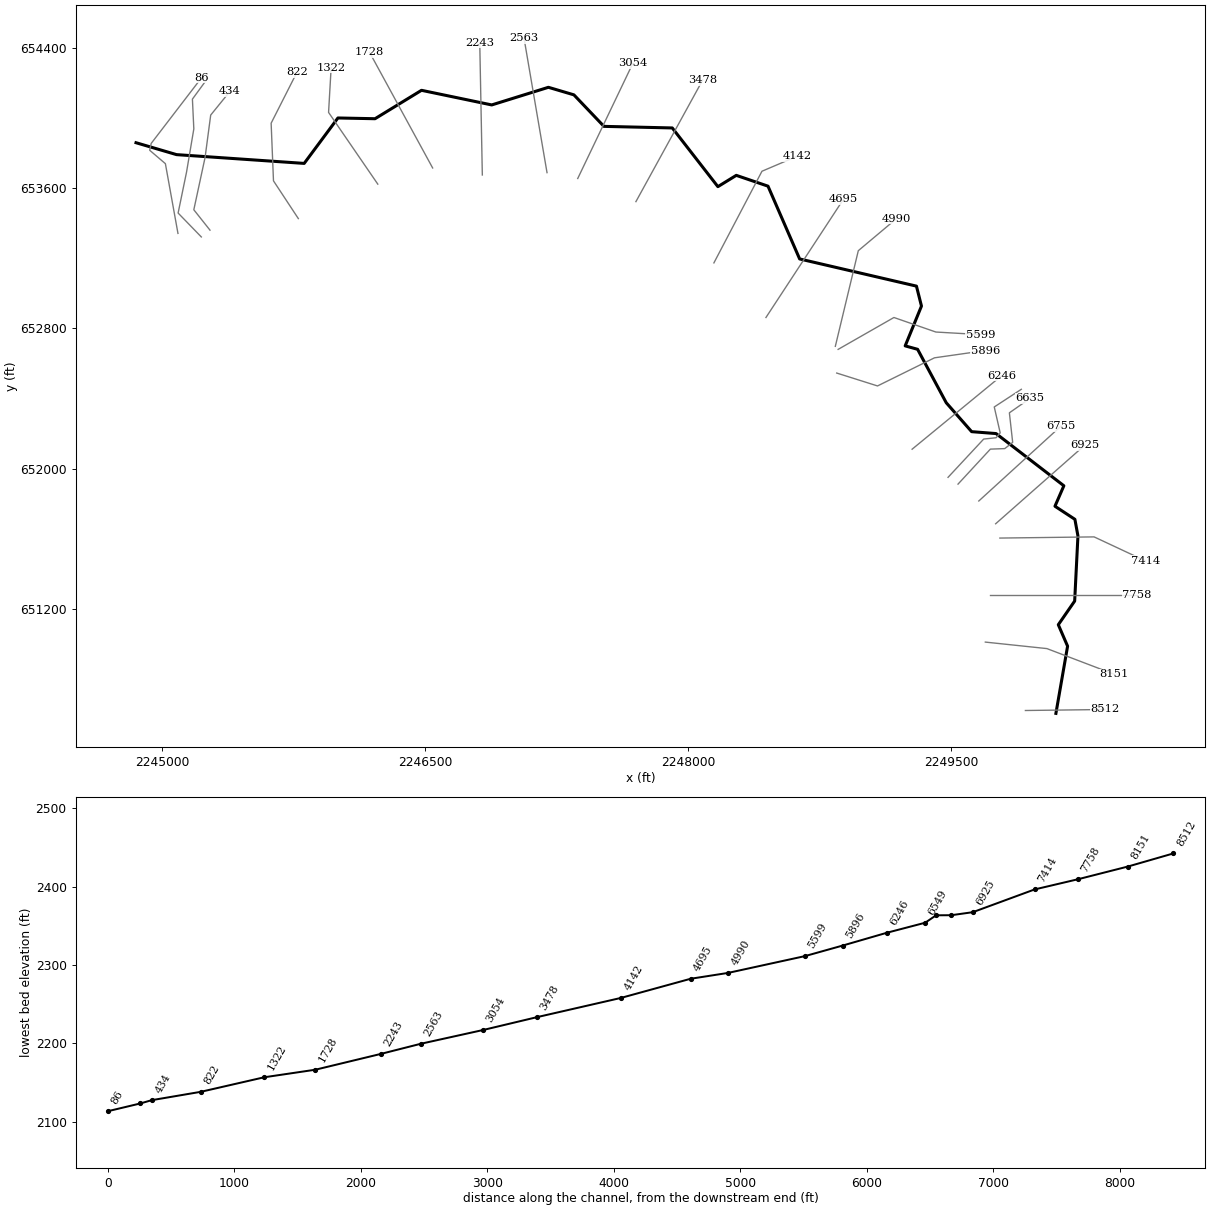
--- STONECLRN.prj (project) ---

Proj Title=STONECLRN
Current Plan=p01
Default Exp/Contr=0,0
English Units
Geom File=g01
Flow File=f01
Plan File=p01
BEGIN DESCRIPTION:
----------MODEL BY WSP USA 2022----------
AFH study
Randolph County, WV
HEC-RAS Version: RAS 6.2
Vertical Datum: NAVD88
Projection: NAD 1983 StatePlane West Virginia S FIPS 4702 (US Feet)
Terrain: 1-meter LIDAR (FEMA Region III 3DEP collected 2016-2018)
Land Use: 2019 NLCD
Hydrologic Method:
WV SIR2010-5033 regression equations
Additional Model Notes:
None
END DESCRIPTION:
DSS Export Rating Curves= 0
DSS Export Rating Curve Sorted= 0
DSS Export Volume Flow Curves= 0
DXF OffsetX= 0
DXF OffsetY= 0
DXF ScaleX= 0
DXF ScaleY= 0

--- STONECLRN.p01 (plan) ---

Plan Title=Floodplain
Program Version=6.20
Short Identifier=Floodplain
Geom File=g01
Flow File=f01
Subcritical Flow
K Sum by GR= 0
Std Step Tol= 0.01
Critical Tol= 0.01
Num of Std Step Trials= 20
Max Error Tol= 0.3
Flow Tol Ratio= 0.001
Split Flow NTrial= 30
Split Flow Tol= 0.02
Split Flow Ratio= 0.02
Log Output Level= 0
Friction Slope Method= 1
Unsteady Friction Slope Method= 2
Unsteady Bridges Friction Slope Method= 1
Parabolic Critical Depth
Global Vel Dist= 0 , 0 , 0
Global Log Level= 0
CheckData=True
Encroach Param=-1 ,0,0, 0
Mapping Interval=1HOUR
Computation Time Step Use Courant=        0
Computation Time Step Use Time Series=    0
Computation Time Step Count To Double=0
Computation Time Step Max Doubling=0
Computation Time Step Max Halving=0
Computation Time Step Residence Courant=0
Run HTab= 0
Run UNet= 0
Run Sediment= 0
Run PostProcess= 0
Run WQNet= 0
Run RASMapper=-1
UNET Theta= 0
UNET Theta Warmup= 0
UNET ZTol= 0
UNET ZSATol= 0
UNET MxIter= 0
UNET Max Iter WO Improvement= 0
UNET MaxInSteps= 0
UNET DtIC= 0
UNET DtMin= 0
UNET MaxCRTS= 0
UNET WFStab= 0
UNET SFStab= 0
UNET WFX= 1
UNET SFX= 1
UNET Gravity=32.174
UNET 1D Methodology=Finite Difference
UNET DSS MLevel= 1
UNET Pardiso=0
UNET DZMax Abort= 0
UNET Use Existing IB Tables= 0
UNET Froude Reduction=False
UNET Froude Limit= 0
UNET Froude Power= 0
UNET D1 Cores= 0
UNET WindReference=Eulerian
UNET WindDragFormulation=Hsu (1988)
UNET D2 Coriolis=0
UNET D2 Cores= 0
UNET D2 Theta= 1
UNET D2 Theta Warmup= 1
UNET D2 Z Tol= 0.01
UNET D2 Volume Tol= 0.01
UNET D2 Max Iterations= 20
UNET D2 Equation= 0
UNET D2 RampUpFraction=0.1
UNET D2 TimeSlices= 1
UNET D2 Turbulence Formulation=Non-Conservative (original)
UNET D2 Eddy Viscosity=0.3
UNET D2 Transverse Eddy Viscosity=0.1
UNET D2 Smagorinsky Mixing=0
UNET D2 BCVolumeCheck=0
UNET D2 Cores=0
UNET D2 SolverType=PARDISO (Direct)
UNET D2 Minimum Iterations= 2147483647
UNET D2 Maximum Iterations= 2147483647
UNET D2 Restart Number= 10
UNET D2 Relaxation Coeff=1.3
UNET D2 SOR Precondition Iterations= 10
UNET D2 ILUT Maximum Fill= 8
UNET D2 ILUT Tolerance=1E-08
UNET D1D2 MaxIter= 0
UNET D1D2 ZTol=0.01
UNET D1D2 QTol=0.1
UNET D1D2 MinQTol=1
Write IC File= 0
Write IC File at Fixed DateTime=0
Write IC File at Sim End=0
Echo Input=False
Echo Parameters=False
Echo Output=False
Write Detailed= 0
HDF Write Warmup=0
HDF Write Time Slices=0
HDF Flush=0
HDF Compression= 1
HDF Chunk Size= 1
HDF Spatial Parts= 1
HDF Use Max Rows=0
HDF Fixed Rows= 1
Calibration Method= 0
Calibration Iterations= 20
Calibration Max Change=0.05
Calibration Tolerance=0.2
Calibration Maximum=1.5
Calibration Minimum=0.5
Calibration Optimization Method= 1
WQ AD Non Conservative
WQ ULTIMATE=-1
WQ Max Comp Step=1HOUR
WQ Output Interval=15MIN
WQ Output Selected Increments= 0
WQ Output face flow=0
WQ Output face velocity=0
WQ Output face area=0
WQ Output face dispersion=0
WQ Output cell volume=0
WQ Output cell surface area=0
WQ Output cell continuity=0
WQ Output cumulative cell continuity=0
WQ Output face conc=0
WQ Output face dconc_dx=0
WQ Output face courant=0
WQ Output face peclet=0
WQ Output face adv mass=0
WQ Output face disp mass=0
WQ Output cell mass=0
WQ Output cell source sink temp=0
WQ Output nsm pathways=0
WQ Output nsm derived pathways=0
WQ Create Restart=0
WQ Fixed Restart=0
WQ System Summary=0
WQ Write To DSS=0
Sorting and Armoring Iterations= 10
XS Update Threshold= 0.02
Bed Roughness Predictor= 0
Hydraulics Update Threshold= 0.02
Energy Slope Method= 1
Volume Change Method= 1
Sediment Retention Method= 0
Sediment TS Multiplier= 1
Warm Up Method= 0
XS Weighting Method= 0
Number of US Weighted Cross Sections= 1
Number of DS Weighted Cross Sections= 1
Upstream XS Weight=0
Main XS Weight=1
Downstream XS Weight=0
Number of DS XS's Weighted with US Boundary= 1
Upstream Boundary Weight= 1
Weight of XSs Associated with US Boundary= 0
Number of US XS's Weighted with DS Boundary= 1
Downstream Boundary Weight= 0.5
Weight of XSs Associated with DS Boundary= 0.5
Percentile Method= 0
Sediment Output Level= 3
Mass or Volume Output= 0
Output Increment Type= 1
Profile and TS Output Increment= 1
Transport Output Increment 1
XS Output Flag= 0
XS Output Increment= 10
Read HDF5 Sediment Hotstart= 0
Sediment Hotstart Type= 0
Write Gradation File= 0
Read Gradation Hotstart= 0
Write HDF5 File= 1
Write Binary Output= 1
Write DSS Sediment File= 0
DSS Sediment Output Type= 1
SV Curve= 0
Specific Gage Flag= 0
Subcell Erosion Methods= 0
Subcell Deposition Methods= 0
Advection Scheme= 1
Matrix Solver= 0
Implicit Weighting Factor= 1
Maximum Outer Loop Convergence Iterations= 5
Convergence Maximum Absolute= 0.001
Convergence RMSE= 0.0001
Grain Fractions Max Abs Error= 0.001
Max Subgrid Regions= 1
Max Subgrid Length Scale= 3.402823E+38
Initial Layer Thickness= 3.402823E+38
Min Layer Thickness= 3.402823E+38
Max Layer Thickness= 3.402823E+38
Number of Layers= 5

--- STONECLRN.f01 (steady flow) ---

Flow Title=Flow
Program Version=6.20
Number of Profiles= 1
Profile Names=P100yr
River Rch & RM=STONECLRN,Main,8512
     351
River Rch & RM=STONECLRN,Main,5896
     505
River Rch & RM=STONECLRN,Main,4990
     647
River Rch & RM=STONECLRN,Main,3478
     722
Boundary for River Rch & Prof#=STONECLRN,Main            , 1
Up Type= 0
Dn Type= 3
Dn Slope=0.04081
DSS Import GetInterval= 0
DSS Import GetPeak= 0
DSS Import FillOption= 0

--- STONECLRN.g01 (geometry) ---

Geom Title=Geometry
Program Version=6.20

River Reach=STONECLRN       ,Main
Reach XY= 30
 2250096.5145215650603.987565178     2250163.133      650987.275
     2250110.182       651109.67     2250203.498      651244.653
     2250222.161      651616.181       2250204.8      651710.799
     2250091.085      651785.452     2250141.866      651902.205
     2249755.147      652199.948     2249615.824      652210.799
     2249471.076      652375.642     2249307.604      652680.573
      2249236.77      652700.104     2249329.696      652927.144
      2249301.05      653040.946     2248634.824      653195.914
2248454.35706507653611.0857027812248273.39521694653672.761838287
     2248168.528      653608.2842247908.33081244653943.131465285
      2247518.55      653952.145     2247347.301      654131.905
     2247201.861      654174.9512246878.55113575654074.392658086
        2246478.      654157.837     2246212.972      653995.784
     2246001.168      654000.001     2245808.806      653740.923
2245080.78876897653790.970260749     2244849.588      653858.927

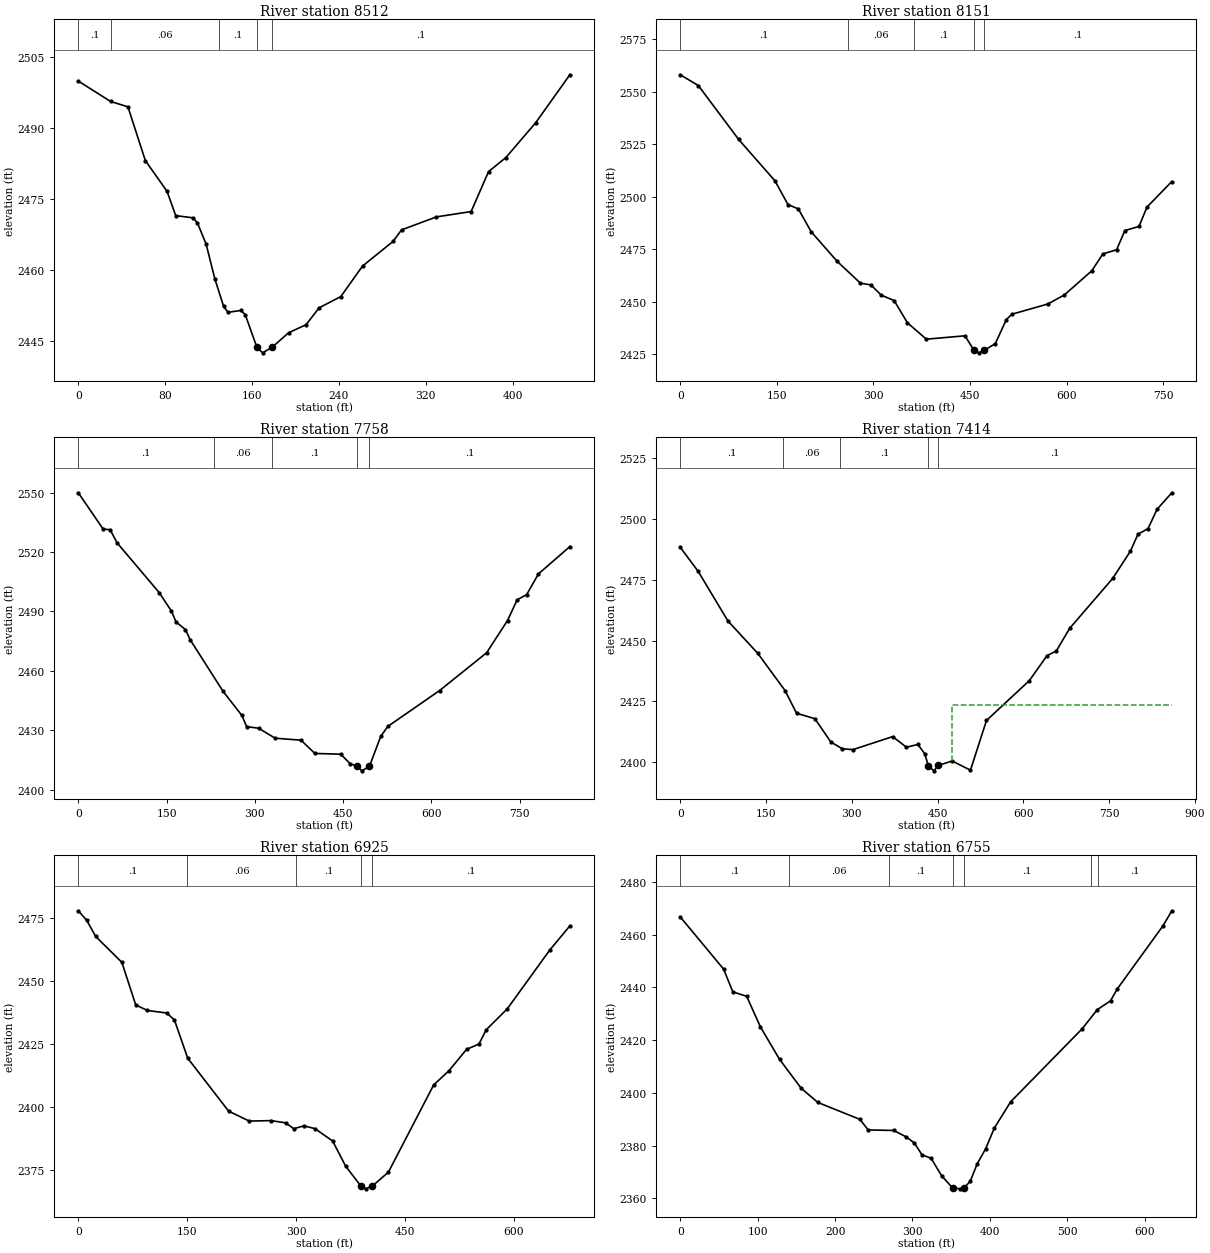
Type RM Length L Ch R = 1 ,8512    ,361.4,360.6,356.5
XS GIS Cut Line= 2
2249922.51811723650620.3682506932250375.08823523650626.116831869
#Sta/Elev= 30
       0 2499.88    29.7 2495.58    45.7 2494.44    61.7  2483.1    81.7 2476.59
    89.7 2471.46   105.7    2471   109.7 2469.92   117.7 2465.44   125.7 2458.12
   133.7 2452.36   137.7 2451.03   149.7 2451.44   153.7 2450.55   164.4 2443.67
   169.7 2442.48  178.52 2443.67   193.7 2446.73   209.7 2448.42   221.7 2451.99
   241.7 2454.36   261.7 2460.81   289.7    2466   297.7 2468.46   329.7 2471.19
   361.7 2472.32   377.7 2480.75   393.7 2483.73   421.2  2491.1   452.6 2501.21
#Mann= 5 ,-1,0
       0      .1       0      30     .06       0     130      .1       0
   164.4    .045       0  178.52      .1       0
Bank Sta=164.4,178.52
XS Rating Curve= 0 ,0
Exp/Cntr(USF)=0,0
Exp/Cntr=0.3,0.1

Type RM Length L Ch R = 1 ,8151    ,389.2,393.6,394.7
XS GIS Cut Line= 3
2249693.89876685651010.5860886192250045.16625436650973.493978785
2250428.21985746650827.483807293
#Sta/Elev= 30
       0 2558.18      28 2553.07    90.7 2527.35   147.1 2507.62   167.2 2496.35
   183.3 2494.28   203.3 2483.37   243.6 2469.29   279.8 2458.87   295.9 2458.07
     312  2453.2   332.1 2450.58   352.6 2440.04   382.1  2432.2   442.1 2433.81
  455.942426.925   463.5 2425.69     472 2426.87   489.1 2430.08   506.3 2441.52
   514.8 2444.08   570.5 2448.95   596.2 2453.24     639 2464.79   656.1 2472.83
   677.5 2474.81   690.3 2483.96   712.2 2485.91   724.6 2495.13   763.2 2507.31
#Mann= 5 ,-1,0
       0      .1       0     260     .06       0  363.22      .1       0
  455.94    .045       0     472      .1       0
Bank Sta=455.94,472
XS Rating Curve= 0 ,0
Exp/Cntr(USF)=0,0
Exp/Cntr=0.3,0.1

Type RM Length L Ch R = 1 ,7758    ,343.1,343.9,343.2
XS GIS Cut Line= 2
 2249722.0838428651277.7066547392250557.67030689651277.706654739
#Sta/Elev= 30
       0 2549.86    42.1  2531.6    54.1 2531.19    66.1 2524.52   137.6 2499.45
   158.1 2490.22   166.1 2484.67   182.1 2480.82   190.1 2475.71   246.1 2449.63
   278.1 2437.46   286.1 2431.85   306.6    2431   334.6 2425.98   378.6 2424.98
   402.1 2418.29   446.1 2417.92   462.1 2413.12   474.6 2411.79   482.1 2409.51
  494.892411.785   514.1 2426.88   526.1 2431.93   614.1 2450.02   694.1 2469.11
   729.6 2485.38   746.1 2495.87   762.1 2498.41   782.1 2508.88   835.6  2522.7
#Mann= 5 ,-1,0
       0      .1       0     230     .06       0     330      .1       0
   474.6    .045       0  494.89      .1       0
Bank Sta=474.6,494.89
XS Rating Curve= 0 ,0
Exp/Cntr(USF)=0,0
Exp/Cntr=0.3,0.1

Type RM Length L Ch R = 1 ,7414    ,478.4,488.8,491.4
XS GIS Cut Line= 3
2249776.89831484651603.9196103192250314.34752855651610.604302032
2250605.80008722651474.236591093
#Sta/Elev= 30
       0 2488.31    31.3 2478.43    83.3 2458.03   135.3 2444.79   183.3 2429.39
   203.3  2420.1   235.3 2417.88   263.3 2408.27   283.3 2405.52   301.8 2405.15
   371.3 2410.51   395.3 2406.16   415.4 2407.28   427.3 2403.46  433.72 2398.52
   443.3 2396.44     451 2398.66   475.3 2400.48   507.3 2396.71   535.3 2417.13
   610.2 2433.52   641.1 2443.77   657.3 2445.68   680.8 2455.03   755.9  2475.5
   786.8 2486.68   800.1 2493.68   817.7 2495.99   833.4 2503.91   859.3 2510.72
#Mann= 5 ,-1,0
       0      .1       0     180     .06       0     280      .1       0
  433.72    .045       0     451      .1       0
#XS Ineff= 2 , 0
                          474.37         2423.45
Permanent Ineff=
       F       F
Bank Sta=433.72,451
XS Rating Curve= 0 ,0
Exp/Cntr(USF)=0,0
Exp/Cntr=0.3,0.1

Type RM Length L Ch R = 1 ,6925    ,169.4,169.9,169.9
XS GIS Cut Line= 2
2249752.83342468651685.4728492152250260.86999484652133.347193967
#Sta/Elev= 30
       0 2477.84    11.7 2474.01    23.8 2467.69      60 2457.36    79.1 2440.46
    95.1 2438.24   121.8 2437.24   132.4  2434.5   150.8 2419.27   207.1 2398.27
   235.5 2394.31   265.7  2394.5   285.6 2393.61   296.9  2391.3   311.1 2392.42
   326.2  2391.3   350.4  2386.4   368.5 2376.36  389.132368.594   396.1  2367.4
  405.222368.529   427.3 2374.03   489.6 2408.65     511 2414.39     535 2422.82
     552 2424.89   562.1  2430.6     591 2438.87   649.7 2462.28   677.3 2471.84
#Mann= 5 ,-1,0
       0      .1       0     150     .06       0     300      .1       0
  389.13    .045       0  405.22      .1       0
Bank Sta=389.13,405.22
XS Rating Curve= 0 ,0
Exp/Cntr(USF)=0,0
Exp/Cntr=0.3,0.1

Type RM Length L Ch R = 1 ,6755    ,122.5,119.8,118.5
XS GIS Cut Line= 2
 2249656.7664704651815.4277900332250126.03182863652243.248059647
#Sta/Elev= 30
       0 2466.79      56 2446.98    67.9 2438.35    85.8 2436.65   103.5 2425.06
   128.2 2412.74   156.2 2401.74   177.8 2396.34     232 2389.93   242.8 2385.92
   275.7 2385.72   291.5 2383.33   302.3    2381   312.3 2376.46     324 2375.16
   337.8 2368.44   351.9 2363.89   361.9 2363.55  366.592363.911   374.6 2366.41
   383.5    2373   394.5 2378.77   405.7 2386.62   426.8  2396.6     519 2424.27
   538.8 2431.61   555.8 2434.94   564.3 2439.35   623.7 2463.48     635 2469.13
#Mann= 7 ,-1,0
       0      .1       0     140     .06       0     270      .1       0
   351.9    .045       0  366.59      .1       0     530     .08       0
     540      .1       0
Bank Sta=351.9,366.59
XS Rating Curve= 0 ,0
Exp/Cntr(USF)=0,0
Exp/Cntr=0.3,0.1

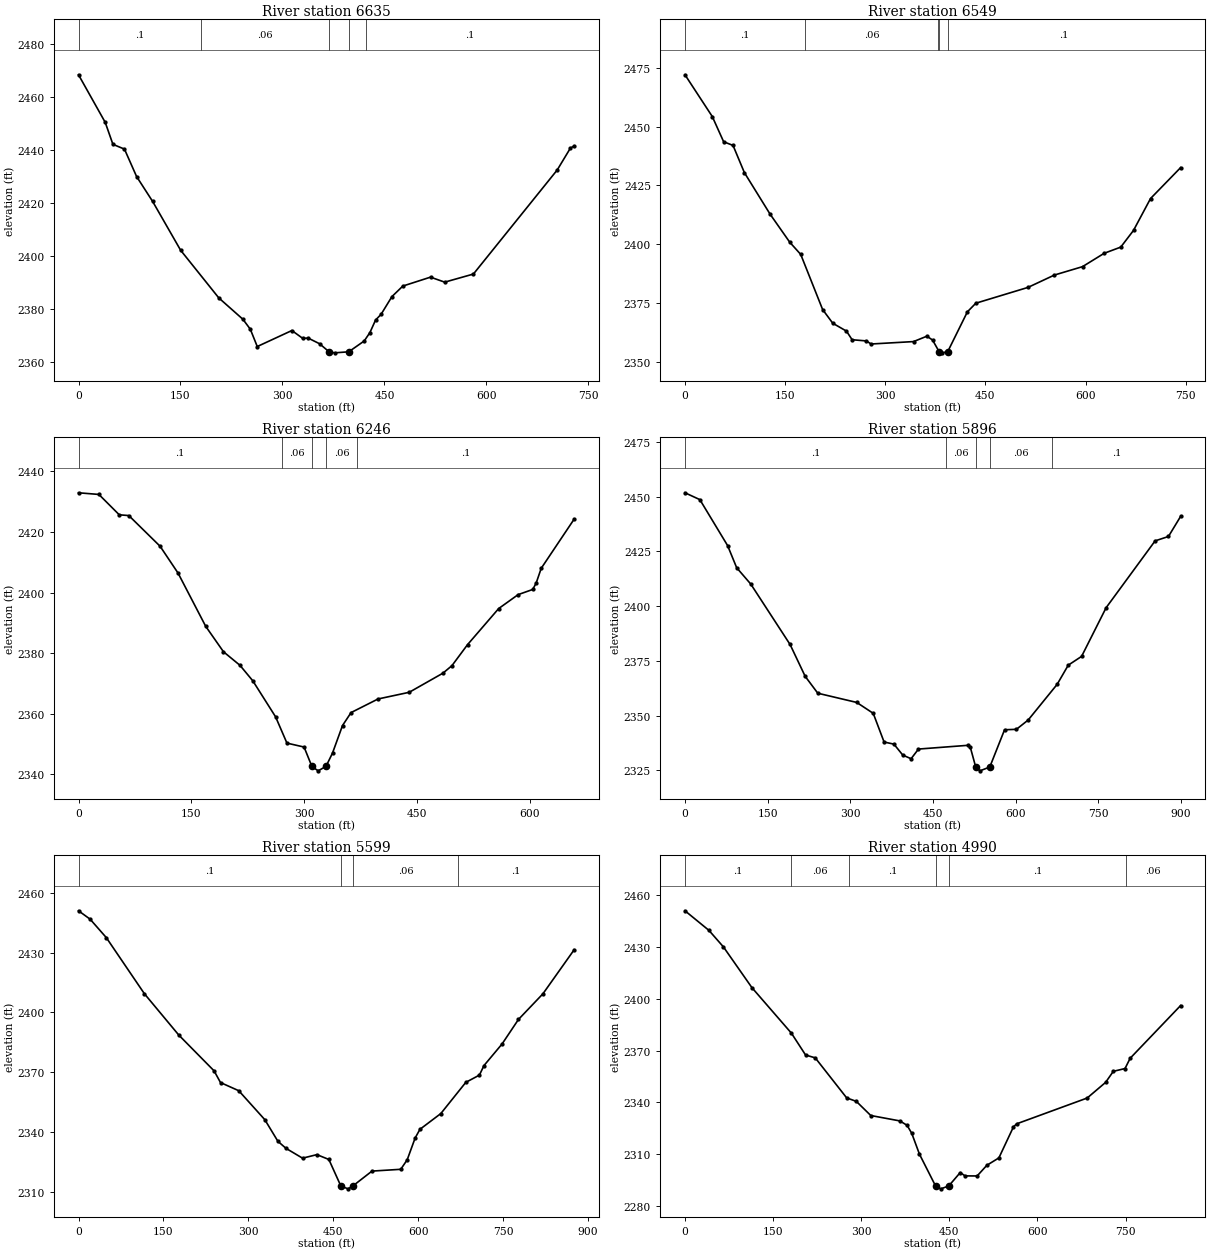
Type RM Length L Ch R = 1 ,6635    ,83.9,86.5,87.9
XS GIS Cut Line= 6
2249538.18656939651911.6462584342249722.68782945652111.208845845
2249804.77206352652114.2211113152249849.95604557652149.615230592
2249831.12938638652318.3020969322249948.60773971652400.386330999
#Sta/Elev= 30
       0  2468.5    39.3 2450.51    50.6 2442.22    67.6 2440.41    85.4 2430.06
     109 2420.65   150.2  2402.2   206.3  2384.2   241.8 2376.12   252.7 2372.36
   262.9 2365.82   313.8 2371.87   329.7 2368.92   337.8 2369.01   354.5 2366.88
   368.5 2363.85   376.8 2363.44  397.45 2363.83   420.2 2367.92   428.6  2371.1
   436.9 2375.83     445 2377.99     461  2384.7     477 2388.67   517.7 2392.04
   538.6 2390.15   580.8 2393.21   704.1 2432.54   723.5 2440.81     729  2441.6
#Mann= 5 ,-1,0
       0      .1       0     180     .06       0   368.5    .045       0
  397.45     .06       0  422.31      .1       0
Bank Sta=368.5,397.45
XS Rating Curve= 0 ,0
Exp/Cntr(USF)=0,0
Exp/Cntr=0.3,0.1

Type RM Length L Ch R = 1 ,6549    ,304.3,302.7,299.2
XS GIS Cut Line= 6
2249481.27621627651950.2549196322249684.60413552652168.644166232
2249755.39237407652176.1748299082249778.73743147652204.038285509
2249744.84944492652351.6392935562249899.22805028652452.550186813
#Sta/Elev= 30
       0    2472    40.9 2454.27    57.9 2443.57      72    2442      89 2430.45
   127.5 2412.82   156.9 2400.93   173.4 2395.72   206.2 2372.32   221.4 2366.51
   241.9 2363.16   250.4  2359.5   271.8    2359   278.7 2357.69   342.4 2358.72
   362.4 2361.01   370.9 2359.37  380.65 2354.47   385.1 2353.94   393.6 2354.45
   423.1 2371.37   435.7 2375.01   513.8 2381.72   553.4 2386.97   595.5 2390.53
     628 2396.21   652.8 2398.83   671.9 2405.92   697.4 2419.45   742.5 2432.59
#Mann= 5 ,-1,0
       0      .1       0     180     .06       0  379.64      .1       0
  380.65    .045       0   393.6      .1       0
Bank Sta=380.65,393.6
XS Rating Curve= 0 ,0
Exp/Cntr(USF)=0,0
Exp/Cntr=0.3,0.1

Type RM Length L Ch R = 1 ,6246    ,350.4,349.6,345.1
XS GIS Cut Line= 2
2249276.36899636652110.7786149332249785.74250487652529.240316149
#Sta/Elev= 30
       0 2432.92    27.1 2432.37    54.2 2425.65    66.9  2425.4   108.5 2415.27
   132.3 2406.45   169.2 2388.83   192.8 2380.45   214.7 2375.98   231.8 2370.86
   262.1 2358.98   277.2  2350.3     300    2349   310.4 2342.59   318.8 2341.15
   329.2 2342.65   337.8 2347.01   351.1  2356.1   362.5 2360.38   398.4 2364.87
   439.8 2367.07   484.7 2373.39   496.7 2375.88   517.4  2382.8   558.8 2394.71
   584.7 2399.31   604.1 2401.01   608.7 2403.15   615.4    2408   659.2 2424.23
#Mann= 5 ,-1,0
       0      .1       0     270     .06       0   310.4    .045       0
   329.2     .06       0     370      .1       0
Bank Sta=310.4,329.2
XS Rating Curve= 0 ,0
Exp/Cntr(USF)=0,0
Exp/Cntr=0.3,0.1

Type RM Length L Ch R = 1 ,5896    ,302.6,297.3,281.3
XS GIS Cut Line= 4
2248846.38922843 652545.124203472249079.01650003 652471.59259463
2249403.89251727652632.025195736 2249694.0081376652673.470284354
#Sta/Elev= 30
       0 2451.72      27 2448.59    77.4 2427.59    93.8  2417.5   119.4 2410.04
   190.7 2382.47   218.1 2367.93     241 2360.22   311.7 2356.01   341.6 2351.04
   361.3 2337.94   379.1 2336.99   395.3 2331.96   410.3 2330.32   423.7 2334.73
   512.9 2336.43   517.8 2335.52  527.34 2326.74   535.2 2324.79   553.1 2326.54
   579.9 2343.54   601.4 2343.74   622.7 2347.97   675.3 2364.26   695.5 2373.03
   719.7 2377.04   764.2 2399.26   853.1 2429.77   877.3 2431.77   899.4 2440.95
#Mann= 5 ,-1,0
       0      .1       0  473.97     .06       0  527.34    .045       0
   553.1     .06       0   666.3      .1       0
Bank Sta=527.34,553.1
XS Rating Curve= 0 ,0
Exp/Cntr(USF)=0,0
Exp/Cntr=0.3,0.1

Type RM Length L Ch R = 1 ,5599    ,589.1,609.3,626.4
XS GIS Cut Line= 4
2248854.41085849652680.1549760672249172.60218401652861.978590653
2249411.91414733652779.0884134152249667.26937075652764.382091647
#Sta/Elev= 30
       0 2450.97    20.5 2446.75      49 2437.53   116.4 2409.31   177.1 2388.57
   239.5 2370.58   250.8 2364.72   283.1 2360.61   329.1 2346.07   352.2 2335.22
   366.5 2331.68   395.7 2326.75   421.1 2328.52   442.2  2326.1   463.4 2312.76
   476.1 2311.35   485.52312.999   518.4 2320.26   569.2 2321.16   580.6 2325.95
   594.6 2336.88   603.1 2341.24     640 2349.16   684.1 2364.82   708.1 2368.45
   716.2 2373.25   748.2 2384.11   777.1 2396.41   820.3 2409.28   875.5 2431.41
#Mann= 4 ,-1,0
       0      .1       0   463.4    .045       0   485.5     .06       0
  669.74      .1       0
Bank Sta=463.4,485.5
XS Rating Curve= 0 ,0
Exp/Cntr(USF)=0,0
Exp/Cntr=0.3,0.1

Type RM Length L Ch R = 1 ,4990    ,298,295.3,290.8
XS GIS Cut Line= 3
2248838.36759838 652697.535174522248969.38755595653243.006018278
2249185.97156744653424.829632864
#Sta/Elev= 30
       0 2451.05    40.8 2439.69    65.5 2430.08     114 2406.47   181.2 2380.09
   205.3 2367.44   221.8 2365.77   275.3 2342.56   291.7 2340.55   316.3 2332.35
   365.8 2329.22   378.1 2326.67     386 2322.07   399.2 2309.92   426.82291.359
   435.6 2289.84     449 2291.51   468.6 2299.28   476.8 2297.35   497.4 2297.31
   513.9 2303.49   534.4 2307.78   559.1 2325.69   564.5 2327.51   684.7 2342.49
   716.1 2351.57   729.2 2357.97   749.1 2359.58   757.9 2365.55   843.8 2396.12
#Mann= 6 ,-1,0
       0      .1       0     180     .06       0     280      .1       0
   426.8    .045       0     449      .1       0  750.99     .06       0
Bank Sta=426.8,449
XS Rating Curve= 0 ,0
Exp/Cntr(USF)=0,0
Exp/Cntr=0.3,0.1

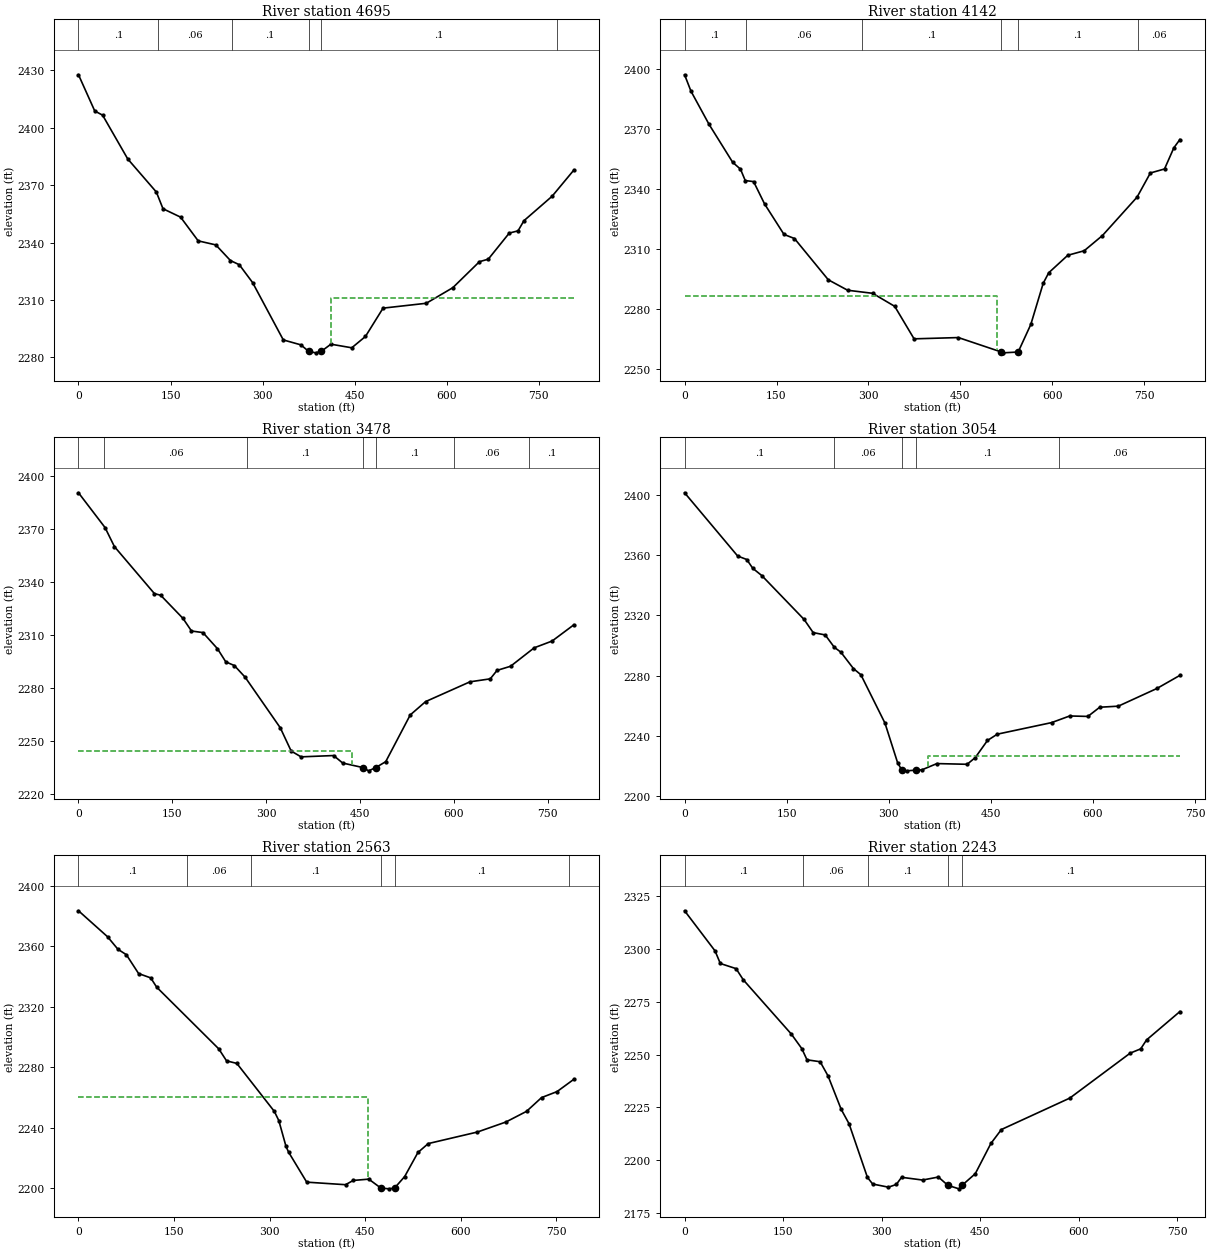
Type RM Length L Ch R = 1 ,4695    ,547.1,552.4,552.9
XS GIS Cut Line= 2
2248442.63384898652861.9785906532248885.16044037653537.132453638
#Sta/Elev= 30
       0 2427.76    26.5 2408.83    39.3 2406.64    80.3 2383.74   126.9 2366.46
   137.7 2357.73   166.4 2353.33   195.1 2340.93   223.8 2338.82   247.7 2330.63
   262.1 2328.45   283.7 2319.15   333.8 2289.14   362.5 2286.56   374.9 2283.21
   386.4 2282.39     396 2283.24   411.4 2286.91   445.4 2285.03   467.7 2290.95
   496.4 2305.76   566.8  2308.3   610.1 2316.45   653.5 2330.05   667.9 2331.36
   702.1    2345   716.4 2346.17     726 2351.46   771.9 2364.25   807.3 2377.92
#Mann= 6 ,-1,0
       0      .1       0     130     .06       0     250      .1       0
   374.9    .045       0     396      .1       0     780     .06       0
#XS Ineff= 2 , 0
                          412.27          2310.9
Permanent Ineff=
       F       F
Bank Sta=374.9,396
XS Rating Curve= 0 ,0
Exp/Cntr(USF)=0,0
Exp/Cntr=0.3,0.1

Type RM Length L Ch R = 1 ,4142    ,661.3,663.9,660.9
XS GIS Cut Line= 3
2248145.83353694653173.4852244662248419.90589716  653696.2281164
2248620.44664854653781.792170323
#Sta/Elev= 30
       0 2397.15    10.4 2388.94      40 2372.27    78.5  2353.3    91.2 2349.88
      99 2344.16   112.6 2343.65   130.6 2332.41   162.2 2317.19   179.3 2315.13
   234.5 2294.46   266.1 2289.22   306.8 2287.69   342.9 2281.16   374.5 2264.88
   446.8 2265.52   517.1 2258.27     520 2257.87  544.342258.281     565 2272.09
   585.2 2292.69   594.2 2297.97   625.3 2306.73   652.1    2309   681.9 2316.63
   738.4 2335.87   760.1 2347.96   783.2 2349.97   798.4 2360.56   808.3 2364.73
#Mann= 6 ,-1,0
       0      .1       0     100     .06       0     290      .1       0
   517.1    .045       0  544.34      .1       0  740.23     .06       0
#XS Ineff= 2 , 0
          509.03 2286.34
Permanent Ineff=
       F       F
Bank Sta=517.1,544.34
XS Rating Curve= 0 ,0
Exp/Cntr(USF)=0,0
Exp/Cntr=0.3,0.1

Type RM Length L Ch R = 1 ,3478    ,425.8,424.6,426.1
XS GIS Cut Line= 2
2247700.94766883653522.8377370832248081.97509645654216.708736863
#Sta/Elev= 30
       0 2390.41    42.4 2370.77    57.4 2360.01   121.3 2333.46   131.4 2332.49
     167 2319.43   180.6 2312.31   198.9 2311.42   222.1 2302.32   235.4 2294.88
   249.1  2292.8   266.3 2286.22   322.5 2257.62   339.9 2244.49   355.7 2241.21
   407.7 2241.95   422.2 2237.72   455.32235.099   463.6 2233.31  474.91 2235.12
     491 2238.49   530.2  2264.9   554.8 2272.44   625.7 2283.61   658.1 2285.29
   668.9 2290.06   690.5 2292.39   728.3 2302.82   756.9 2306.64   791.6  2315.8
#Mann= 7 ,-1,0
       0      .1       0      40     .06       0     270      .1       0
   455.3    .045       0  474.91      .1       0     600     .06       0
     720      .1       0
#XS Ineff= 2 , 0
           436.5  2244.4
Permanent Ineff=
       F       F
Bank Sta=455.3,474.91
XS Rating Curve= 0 ,0
Exp/Cntr(USF)=0,0
Exp/Cntr=0.3,0.1

Type RM Length L Ch R = 1 ,3054    ,484.8,491,498.3
XS GIS Cut Line= 2
2247369.07235992653654.7830277812247683.25287042 654311.21975397
#Sta/Elev= 30
       0 2401.26      78 2359.33    91.3 2357.03   100.2 2351.18   113.5 2346.35
   175.6 2317.29   188.9 2308.58   206.6 2307.03   219.9 2298.87   229.6  2295.6
   248.1 2284.72     259 2280.64   294.4 2248.57   312.9  2222.4     319 2217.53
   326.4 2216.95   339.7 2217.41   348.6 2217.61   370.7 2221.76   415.1 2221.29
     427 2225.71     445 2237.09   459.4 2241.25   539.2 2248.92   565.8 2253.32
   592.5 2253.02   609.9 2259.11   637.2 2259.82   693.9 2271.54   727.7 2280.23
#Mann= 5 ,-1,0
       0      .1       0     220     .06       0     319    .045       0
   339.7      .1       0     550     .06       0
#XS Ineff= 2 , 0
                          357.87         2226.57
Permanent Ineff=
       F       F
Bank Sta=319,339.7
XS Rating Curve= 0 ,0
Exp/Cntr(USF)=0,0
Exp/Cntr=0.3,0.1

Type RM Length L Ch R = 1 ,2563    ,321.3,319.6,318.1
XS GIS Cut Line= 2
2247193.93343705653688.2064863452247062.91347948654454.272156622
#Sta/Elev= 30
       0 2383.54    45.6 2366.34    61.9 2358.05    75.1 2354.45    94.3 2341.98
   113.3 2339.11   122.7 2332.95   220.1 2292.11   232.3 2284.18   248.5 2282.47
   307.3  2250.7   314.3 2244.65   325.6 2227.53   329.7 2223.69   358.1 2203.86
     419 2202.17   431.1 2204.99   455.5 2205.85  474.432199.951   487.5 2199.43
   496.1 2200.03   511.8 2207.57   532.6  2223.5   548.8  2229.4   625.9 2237.04
   670.6 2243.67     703 2250.73   726.6 2259.85   750.9 2263.82   777.2 2271.94
#Mann= 6 ,-1,0
       0      .1       0     170     .06       0     270      .1       0
  474.43    .045       0   496.1      .1       0     770     .06       0
#XS Ineff= 2 , 0
          454.01 2260.34
Permanent Ineff=
       F       F
Bank Sta=474.43,496.1
XS Rating Curve= 0 ,0
Exp/Cntr(USF)=0,0
Exp/Cntr=0.3,0.1

Type RM Length L Ch R = 1 ,2243    ,509.8,515.7,520.9
XS GIS Cut Line= 2
2246824.93845451653674.8371029192246810.23213274654428.870328114
#Sta/Elev= 30
       0 2318.15    46.4 2299.12    54.4 2293.16    78.4 2290.72    89.4 2285.41
   162.4 2259.75   178.4 2252.85   186.4 2247.49   206.4 2246.59   218.4 2239.88
   238.5 2223.98   250.4 2217.19   278.4 2191.76   286.4 2188.61   310.4 2187.12
   322.4 2188.41   330.4  2191.8   362.4  2190.5   386.4 2191.93  400.98 2187.98
   417.8 2186.33   422.9 2188.11   442.6 2193.49   466.4 2207.84   482.4 2214.45
   586.5 2229.34   678.5 2250.66   694.5 2252.69   703.4 2256.92   754.2 2270.38
#Mann= 5 ,-1,0
       0      .1       0     180     .06       0     280      .1       0
  400.98    .045       0   422.9      .1       0
Bank Sta=400.98,422.9
XS Rating Curve= 0 ,0
Exp/Cntr(USF)=0,0
Exp/Cntr=0.3,0.1

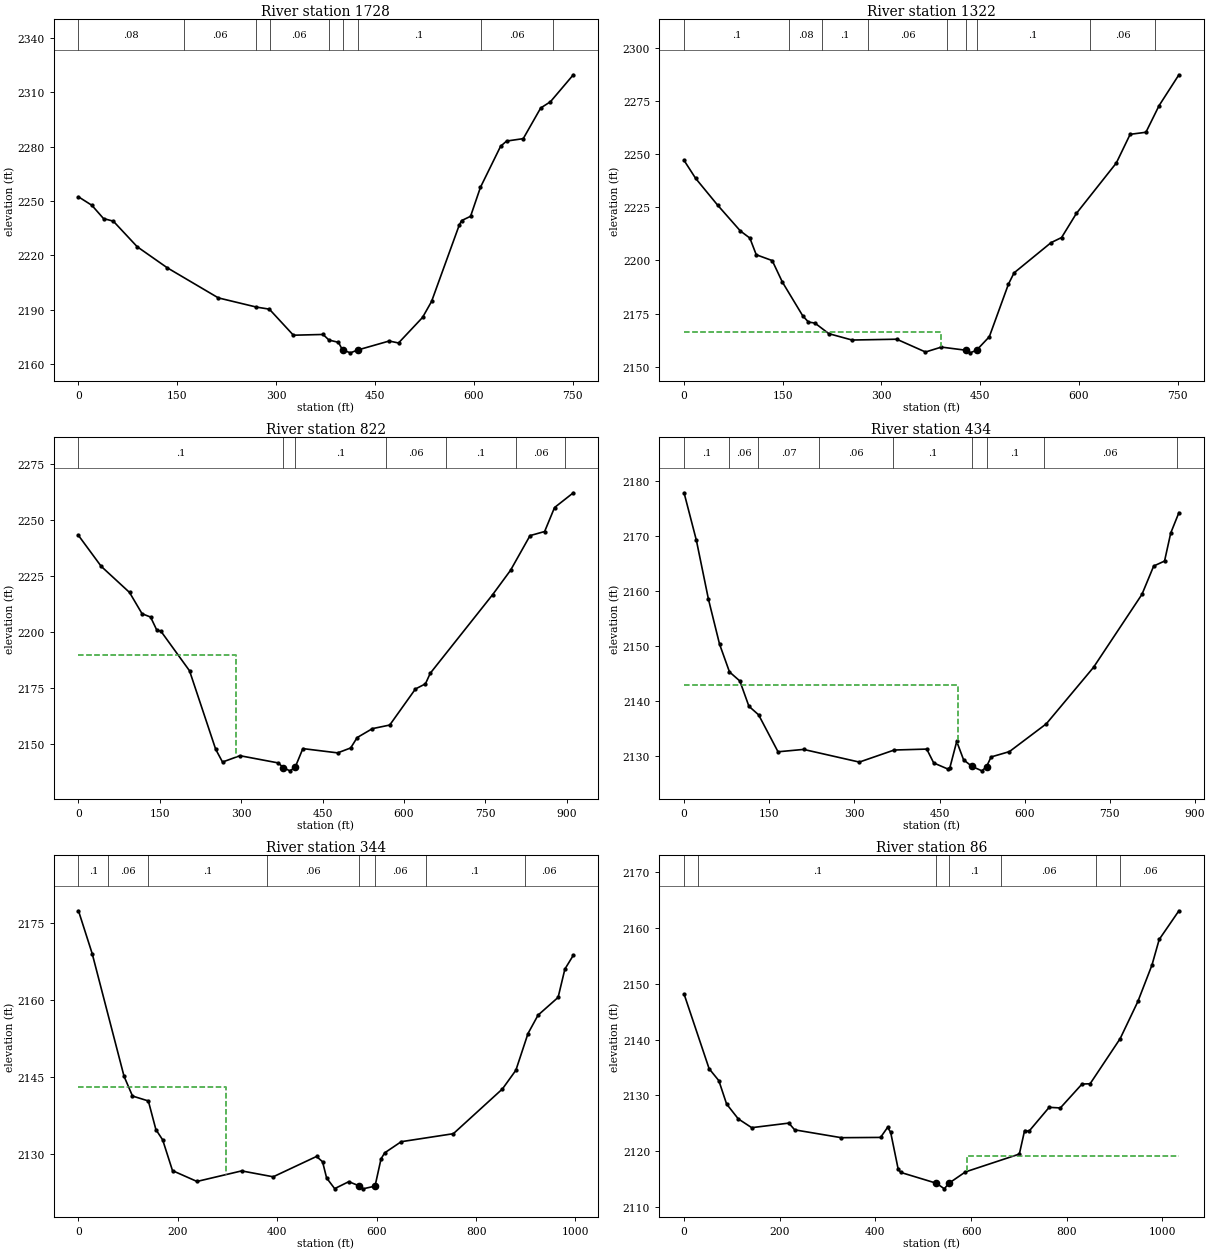
Type RM Length L Ch R = 1 ,1728    ,402.9,405.5,402.6
XS GIS Cut Line= 2
2246541.50752589653714.9452531962246181.87111174 654374.05585607
#Sta/Elev= 30
       0 2252.29    20.3 2247.62      38  2240.3    52.9 2238.85    89.1 2224.76
   134.7 2213.15   212.2 2196.54     270 2191.47   289.6 2190.32   326.1 2175.95
   371.1 2176.37     380 2173.29   394.4 2172.02   400.6 2167.85   412.6 2166.23
   423.5 2167.78   471.4 2172.75   485.6 2171.67     522 2185.74   535.7 2194.55
   577.5 2236.48   581.2 2239.16   594.9 2241.55   609.9 2257.55   640.5  2280.2
   649.6 2283.05   674.8 2284.38   701.3 2301.29   716.1 2304.74   750.8 2319.61
#Mann= 9 ,-1,0
       0     .08       0     160     .06       0     270      .1       0
     290     .06       0     380      .1       0   400.6    .045       0
   423.5      .1       0     610     .06       0     720      .1       0
Bank Sta=400.6,423.5
XS Rating Curve= 0 ,0
Exp/Cntr(USF)=0,0
Exp/Cntr=0.3,0.1

Type RM Length L Ch R = 1 ,1322    ,504.7,500.6,492.6
XS GIS Cut Line= 3
2246228.66395373 653622.69650756 2245947.9069018654031.799640379
2245962.61322357654287.154863805
#Sta/Elev= 30
       0 2246.97    17.6 2238.52      51 2225.95    85.6  2213.8     100 2210.47
   109.7 2202.64     134 2199.89   149.3 2189.85   180.5 2173.86   189.1    2171
   198.8 2170.54     220 2165.55   255.3 2162.56   323.2 2162.94   366.9 2156.93
   391.1 2159.24   427.9 2157.78   434.8 2156.54   444.5 2157.78   463.9 2164.11
     493 2188.86   501.5 2194.12   557.7 2208.32   573.7 2210.72   596.2 2222.05
   656.9 2245.76   677.9 2259.22   701.9 2260.19   721.9 2272.73     752  2287.2
#Mann= 9 ,-1,0
       0      .1       0     160     .08       0     210      .1       0
     280     .06       0     400      .1       0   427.9    .045       0
   444.5      .1       0  616.18     .06       0  716.18      .1       0
#XS Ineff= 2 , 0
          390.26 2166.31
Permanent Ineff=
       F       F
Bank Sta=427.9,444.5
XS Rating Curve= 0 ,0
Exp/Cntr(USF)=0,0
Exp/Cntr=0.3,0.1

Type RM Length L Ch R = 1 ,822     ,389,387.7,385.5
BEGIN DESCRIPTION:
Structure XS 4
END DESCRIPTION:
XS GIS Cut Line= 4
2245775.44185561653426.166571206 2245633.7263913653641.413644356
2245620.35700787653970.3004766222245767.42022555654260.416096954
#Sta/Elev= 30
       0  2243.1    41.9  2229.3    94.1 2217.65   117.2 2208.14   132.9 2206.66
   144.1 2200.96   152.1 2200.29   204.7 2182.67   252.9 2147.62   265.5 2141.92
   297.6 2144.75   368.5 2141.51   377.6 2139.37   389.8 2137.99  399.382139.571
   413.6 2147.92   477.7 2146.01   501.7 2148.21   513.7 2152.85   541.7 2156.83
   573.7 2158.44   621.1 2174.55   639.5 2176.83   648.4 2181.56   763.4 2216.67
   796.4 2227.55   832.3 2243.02   859.2 2244.85   877.5 2255.56   912.1 2262.15
#Mann= 7 ,-1,0
       0      .1       0   377.6    .045       0  399.38      .1       0
  567.71     .06       0  676.87      .1       0  806.87     .06       0
  896.87      .1       0
#XS Ineff= 2 , 0
          290.25 2189.79
Permanent Ineff=
       F       F
Bank Sta=377.6,399.38
XS Rating Curve= 0 ,0
Exp/Cntr(USF)=0,0
Exp/Cntr=0.3,0.1

Type RM Length L Ch R = 1 ,434     ,90.6,89.7,88.3
BEGIN DESCRIPTION:
Structure XS 3
END DESCRIPTION:
XS GIS Cut Line= 5
2245271.59128909653360.1775464772245179.34254346653476.491182278
 2245243.5155839653774.6284326652245275.60210412654016.614272666
2245385.23104821654151.645045263
#Sta/Elev= 30
       0 2177.82    21.7 2169.19      43 2158.47    62.5 2150.34      80 2145.29
    98.3 2143.64   114.2 2139.06   131.3  2137.5   165.5 2130.79   210.5 2131.22
   308.7 2128.92   370.1 2131.11   427.4 2131.28   439.7 2128.76   464.1 2127.68
   468.1 2127.88   480.2 2132.67   492.3 2129.33  506.912128.141   524.6 2127.33
   532.7 2128.09   540.7 2129.85     573 2130.82     638 2135.87   721.1 2146.12
   806.4 2159.37   827.1 2164.52   846.2 2165.42   857.1 2170.51   871.5 2174.21
#Mann= 9 ,-1,0
       0      .1       0      80     .06       0     130     .07       0
  238.45     .06       0  368.45      .1       0  506.91    .045       0
   532.7      .1       0  633.42     .06       0  867.52      .1       0
#XS Ineff= 2 , 0
          481.59 2142.86
Permanent Ineff=
       F       F
Bank Sta=506.91,532.7
XS Rating Curve= 0 ,0
Exp/Cntr(USF)=0,0
Exp/Cntr=0.3,0.1

Type RM Length L Ch R = 1 ,344     ,256.1,258,258.4
BEGIN DESCRIPTION:
Structure XS 2
END DESCRIPTION:
XS GIS Cut Line= 6
2245222.12457042653321.406334543 2245089.7676745653457.774045483
2245137.89745484653691.7382554282245179.34254346653937.734910456
 2245171.3209134654107.5260799592245258.22190567654226.513592446
#Sta/Elev= 30
       0 2177.42    27.6 2169.06    91.7 2145.12   108.7 2141.27   140.6 2140.31
   155.8 2134.72   169.4 2132.72   189.2 2126.71   238.4  2124.6   328.3 2126.66
   391.8 2125.51     479 2129.48   491.1 2128.45   499.3 2125.28   515.5  2123.2
   543.9 2124.56  564.22 2123.76   572.3 2123.16   596.7 2123.69   608.8 2129.01
   616.1 2130.18   649.4 2132.36   754.3 2133.92     853 2142.65   880.1  2146.3
   904.5 2153.47   924.7 2157.05   965.1 2160.52   978.7 2166.04   995.7 2168.74
#Mann= 8 ,-1,0
       0      .1       0      60     .06       0     140      .1       0
  380.04     .06       0  564.22    .045       0   596.7     .06       0
  698.37      .1       0  898.35     .06       0
#XS Ineff= 2 , 0
          296.75 2142.97
Permanent Ineff=
       F       F
Bank Sta=564.22,596.7
XS Rating Curve= 0 ,0
Exp/Cntr(USF)=0,0
Exp/Cntr=0.3,0.1

Type RM Length L Ch R = 1 ,86      ,,,
BEGIN DESCRIPTION:
Structure XS 1
END DESCRIPTION:
XS GIS Cut Line= 5
2245088.87798983 653341.650992422245017.17382686653739.403043669
2244927.70145964653815.7749565662244936.26629716 653854.99690387
2245223.67725788654229.828832346
#Sta/Elev= 30
       0 2148.17    52.4 2134.76    72.7 2132.62    88.9 2128.43   113.3 2125.76
   141.4 2124.18     219    2125   231.2 2123.79   328.7 2122.38   410.7 2122.43
   425.4 2124.23   431.8 2123.36   447.5 2116.76   452.8 2116.15   527.6  2114.2
     544  2113.2   553.42114.192   588.1 2116.24   700.8 2119.44   711.8 2123.67
     721 2123.54   763.1 2127.83   786.5 2127.72   831.8 2132.01   848.7 2132.06
   911.5 2140.16   948.6 2146.84     978 2153.37   993.1 2157.96  1034.3 2163.11
#Mann= 7 ,-1,0
       0     .06       0      30      .1       0   527.6    .045       0
   553.4      .1       0   661.5     .06       0   861.5      .1       0
   911.5     .06       0
#XS Ineff= 2 , 0
                           591.4         2119.03
Permanent Ineff=
       F       F
Bank Sta=527.6,553.4
XS Rating Curve= 0 ,0
Exp/Cntr(USF)=0,0
Exp/Cntr=0.3,0.1
LCMann Table=0

Chan Stop Cuts=-1
Use User Specified Reach Order=0
Composite Channel Slope=5